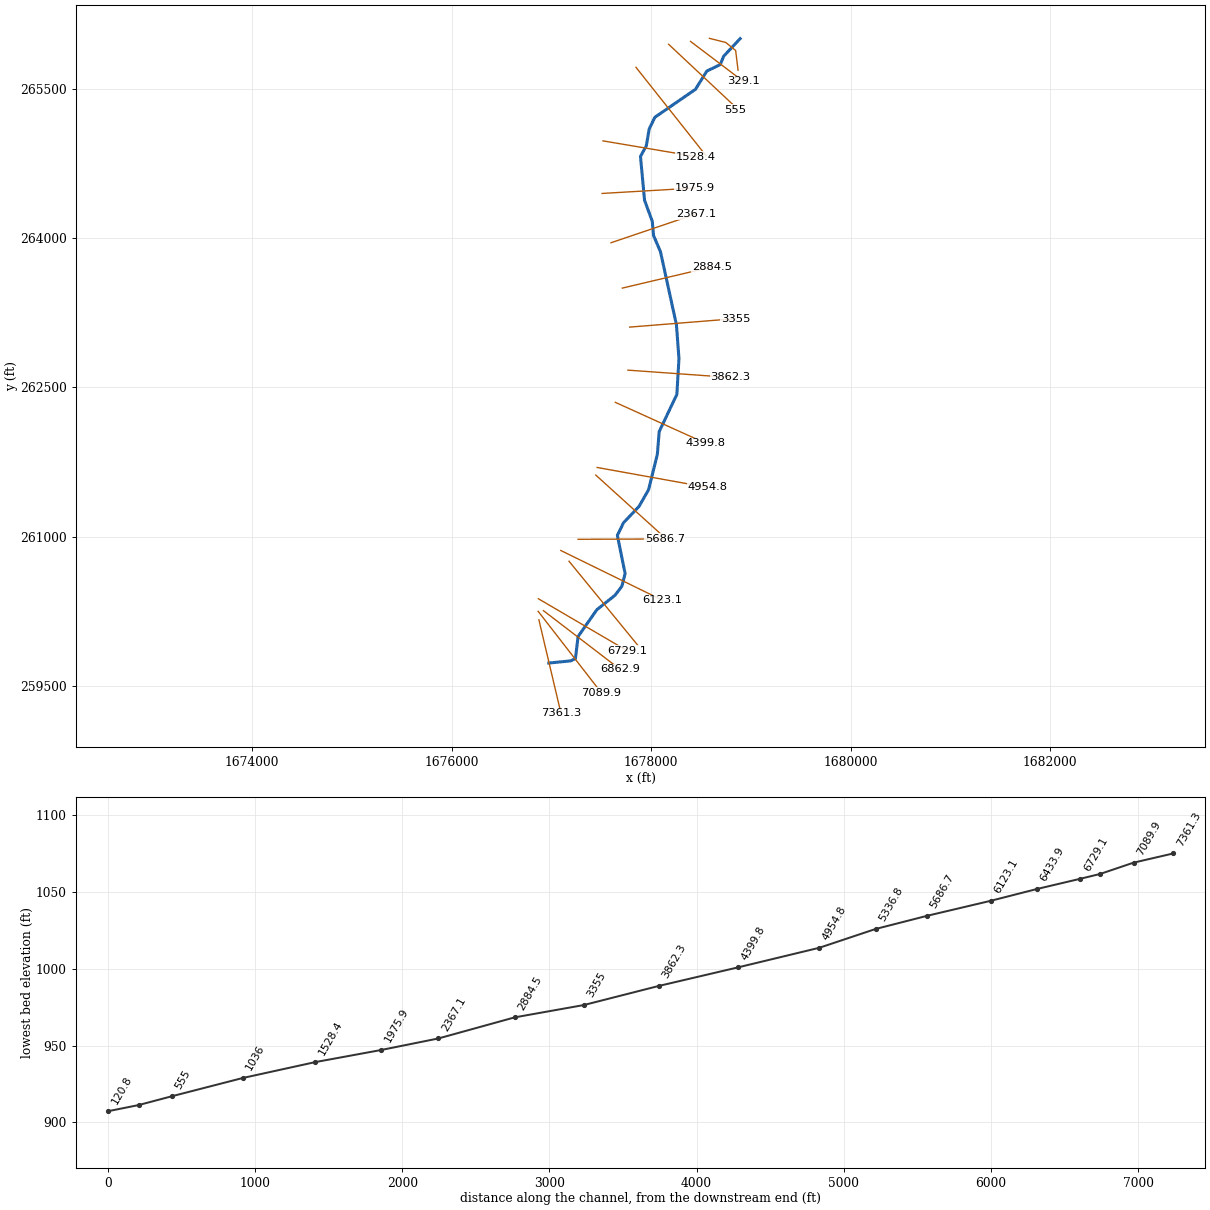
--- LITTLESCRK.prj (project) ---

Proj Title=LITTLESCRK
Current Plan=p01
Default Exp/Contr=0,0
English Units
Geom File=g01
Flow File=f01
Plan File=p01
BEGIN DESCRIPTION:
END DESCRIPTION:
DSS Export Rating Curves= 0
DSS Export Rating Curve Sorted= 0
DSS Export Volume Flow Curves= 0
DXF OffsetX= 0
DXF OffsetY= 0
DXF ScaleX= 0
DXF ScaleY= 0

--- LITTLESCRK.p01 (plan) ---

Plan Title=Floodplain
Program Version=4.00
Geom File=g01
Flow File=f01
K Sum by GR=0
Std Step Tol=0.01
Critical Tol=0.01
Num of Std Step Trials=20
Max Error Tol=0.3
Flow Tol Ratio=0.001
Split Flow NTrial=30
Split Flow Tol=0.02
Split Flow Ratio=0.02
Log Output Level=0
Friction Slope Method=1
Unsteady Friction Slope Method=2
Unsteady Bridges Friction Slope Method=1
Global Log Level=0
CheckData=False
Run HTab=0
Run UNet=0
Run PostProcess=0
UNET Theta=0
UNET Theta Warmup=0
UNET ZTol=0
UNET ZSATol=0
UNET MxIter=0
UNET MaxInSteps=0
UNET DtIC=0
UNET DtMin=0
UNET MaxCRTS=0
UNET WFStab=0
UNET SFStab=0
UNET WFX=0
UNET SFX=0
UNET DSS MLevel=0
UNET DZMax Abort=0
UNET Convert EG Bridges=0
UNET Use Existing IB Tables=0
UNET Froude Limit=0
UNET Froude Power=0
Write IC File=0
Echo Input=False
Echo Output=False
Write Detailed=0

--- LITTLESCRK.f01 (steady flow) ---

Flow Title=NFF Regression Equation
Program Version=4.00
Number of Profiles=1
Profile Names=P100yr
River Rch & RM=LITTLESCRK,Main      ,7361.3
888.6882
River Rch & RM=LITTLESCRK,Main      ,6433.9
959.2291
River Rch & RM=LITTLESCRK,Main      ,5686.7
1004.888
River Rch & RM=LITTLESCRK,Main      ,5336.8
1098.750
River Rch & RM=LITTLESCRK,Main      ,2884.5
1149.540
River Rch & RM=LITTLESCRK,Main      ,120.8
1273.303
Boundary for River Rch & Prof#=LITTLESCRK,Main      ,1
Up Type=0
Dn Type=3
Dn Slope=0.025166

--- LITTLESCRK.g01 (geometry) ---

Geom Title=USGS 10m DEM
Program Version=4.10

River Reach=LITTLESCRK      ,Main
Reach XY= 30
      1676973.04       259732.17     1677194.257      259754.176
     1677240.585       259777.34     1677267.223      259998.557
     1677454.852       260267.26     1677637.848      260413.193
     1677706.183      260503.533     1677738.612      260630.936
     1677661.013      261014.301     1677722.397      261140.545
     1677878.755      261306.168     1677973.727      261472.949
     1678061.751      261828.518     1678080.282      262056.684
     1678257.487      262430.784     1678278.335      262789.826
     1678252.854      263130.338     1678093.022      263863.481
      1678023.53      264025.629      1678010.79      264169.246
      1677933.19      264381.197     1677892.653      264820.156
     1677950.563      264925.553     1677980.677      265098.125
     1678037.429      265213.946     1678443.958       265494.23
     1678557.462      265677.227     1678692.972      265743.244
     1678726.559      265826.635     1678891.263      266003.301

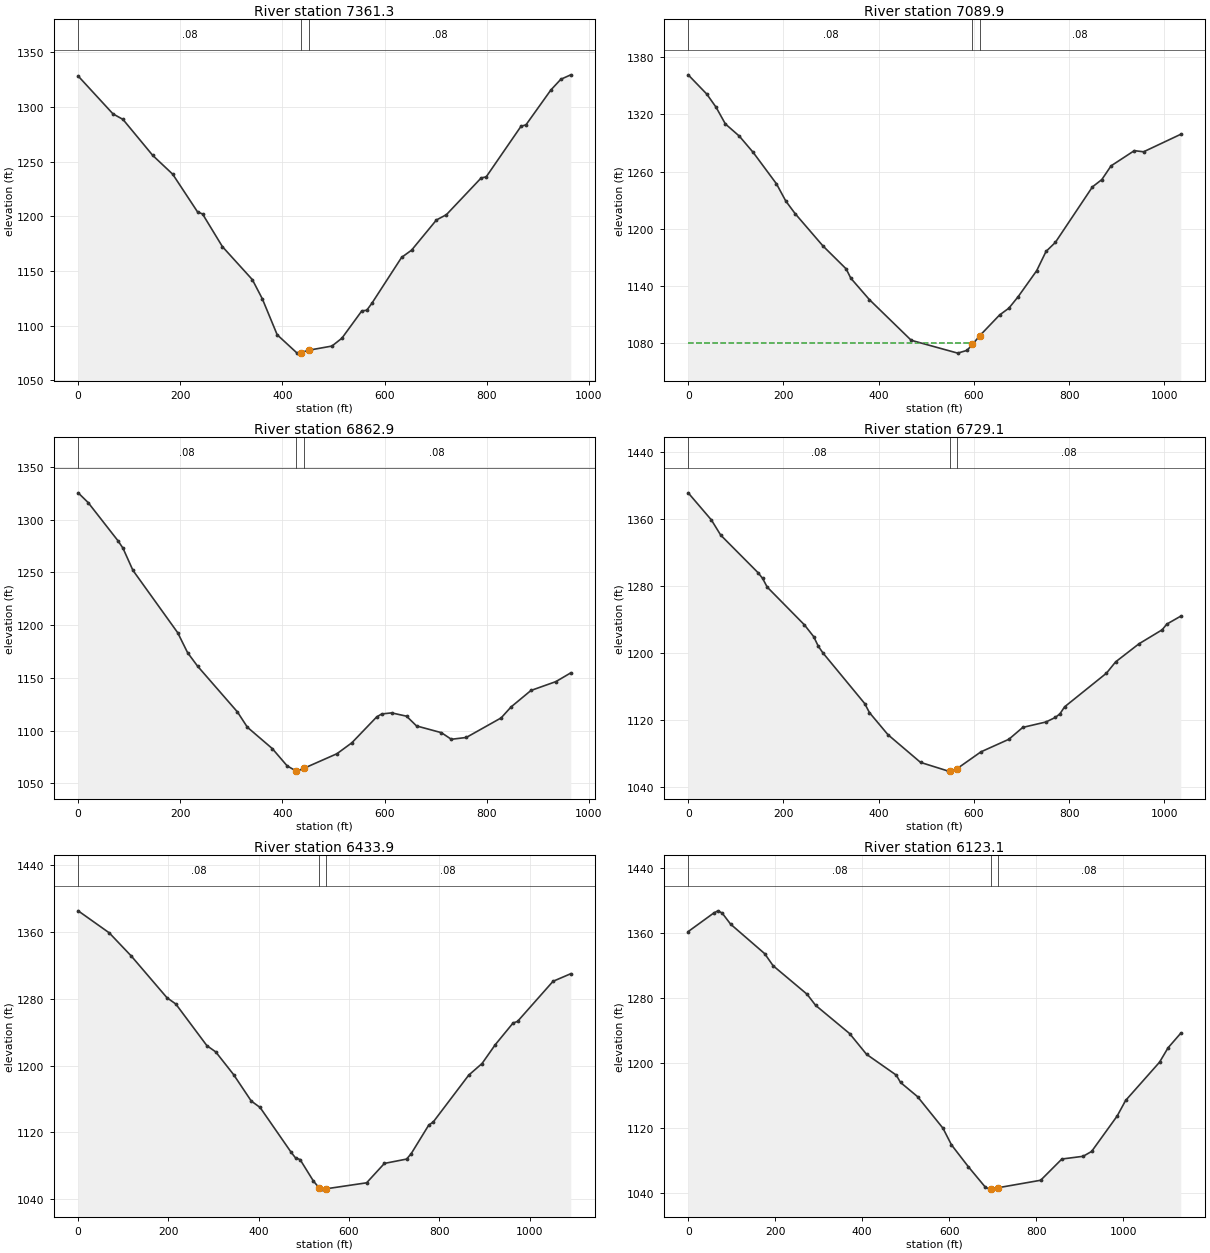
Type RM Length L Ch R = 1 ,7361.3  ,261.5,271.3,281.3
XS GIS Cut Line= 2
     1676874.568      260165.681     1677096.034      259226.635
#Sta/Elev= 30
       0 1328.29    68.2 1293.68    87.7 1288.65   146.2 1255.63   185.2  1238.5
   233.9 1203.99   243.6 1202.16   282.6 1172.22   341.1 1142.13   360.6 1124.66
   389.8 1091.68   428.8  1074.9   436.3 1075.37   451.3 1077.55     497 1081.36
   516.5 1088.53   555.5  1113.5   565.2 1114.12     575 1120.31   633.5 1162.46
     653 1169.06   701.7 1196.67   721.2  1201.5   789.4 1235.15   799.1 1236.04
   867.4 1282.37   877.1 1283.68   925.8 1315.53   945.3 1325.32   964.8  1329.4
#Mann= 3 , 0 , 0
       0     .08       0   436.3    .045       0   451.3     .08       0
Bank Sta=436.3,451.3
XS Rating Curve= 0 ,0
Exp/Cntr=0.3,0.1

Type RM Length L Ch R = 1 ,7089.9  ,221.1,227,232.8
XS GIS Cut Line= 2
     1676866.909       260251.77      1677500.29      259433.862
#Sta/Elev= 30
       0 1361.74      39  1341.5    58.6 1327.61    78.1 1310.06   107.4 1297.23
   136.6 1280.05   185.4 1247.04   204.9    1229   224.5 1215.75     283 1181.68
   331.8  1157.5   341.6 1147.67   380.6 1125.16   468.4 1082.38     566 1068.88
   585.6  1071.8     597 1078.06     612 1087.05   653.9    1109   673.4 1116.16
   692.9 1128.23   731.9 1155.66   751.5  1175.9     771 1185.34     849 1243.84
   868.6 1251.47   888.1 1265.95   936.9 1281.94   956.4 1280.75  1034.5 1299.19
#Mann= 3 , 0 , 0
       0     .08       0     597    .045       0     612     .08       0
#XS Ineff= 2 , 0
          594.15 1079.55
Permanent Ineff=
       F       F
Bank Sta=597,612
XS Rating Curve= 0 ,0
Exp/Cntr=0.3,0.1

Type RM Length L Ch R = 1 ,6862.9  ,131.1,133.8,136.5
XS GIS Cut Line= 2
     1676920.535      260257.915     1677685.982      259670.592
#Sta/Elev= 30
       0 1325.59    19.5 1316.37      78 1280.09    87.7 1273.13   107.2  1252.1
   194.9  1192.9   214.4 1173.87   233.9 1161.13   311.9 1117.72   331.4  1103.2
   380.1 1082.98   409.3 1066.53   426.7 1061.71   428.8 1061.54   441.7 1064.13
   506.8 1078.04     536 1088.41   584.7 1112.98   594.5 1115.77     614 1116.81
   643.2 1113.66   662.7 1104.43   711.4 1098.02   730.9 1091.74   760.2 1093.49
   828.4 1112.03   847.9 1122.45   886.8 1138.06   935.6 1146.47   964.8 1154.77
#Mann= 3 , 0 , 0
       0     .08       0   426.7    .045       0   441.7     .08       0
Bank Sta=426.7,441.7
XS Rating Curve= 0 ,0
Exp/Cntr=0.3,0.1

Type RM Length L Ch R = 1 ,6729.1  ,303.3,295.3,287.3
XS GIS Cut Line= 2
     1676869.227      260378.026     1677761.441      259854.481
#Sta/Elev= 30
       0 1390.81    48.8 1358.36    68.3  1340.3   146.4 1295.61   156.2 1288.69
   165.9 1278.27     244 1233.18   263.5  1219.1   273.3 1207.55     283 1199.59
   370.8 1139.08   380.6 1128.37   419.6 1101.92     488 1068.85   546.5 1058.43
   549.9 1058.68   564.9 1061.48   614.8 1081.45   673.4 1096.46   702.7 1110.66
   751.5 1117.15     771 1122.55   780.7 1126.87   790.5 1135.22   878.3 1175.37
   897.8 1188.98   946.6 1210.46   995.4 1227.24  1005.2 1234.03  1034.5 1243.56
#Mann= 3 , 0 , 0
       0     .08       0   549.9    .045       0   564.9     .08       0
Bank Sta=549.9,564.9
XS Rating Curve= 0 ,0
Exp/Cntr=0.3,0.1

Type RM Length L Ch R = 1 ,6433.9  ,301.2,310.8,320.4
XS GIS Cut Line= 2
     1677176.545      260754.431     1677866.971      259909.121
#Sta/Elev= 30
       0 1385.58    68.8 1359.18     118 1331.17   196.7 1281.37   216.3 1273.84
   285.2 1223.86   304.8 1216.38   344.2 1189.26   383.5 1157.45   403.1 1149.69
     472 1095.85   481.8 1089.07   491.6  1087.3   521.1 1061.56   533.7 1053.39
   540.8 1051.77   548.7 1052.11   639.1 1059.36   678.5 1082.61   727.6 1087.81
   737.5 1094.02   776.8 1128.64   786.6 1132.24   865.3 1188.49   894.8 1202.43
   924.3 1225.15   963.6 1251.04   973.4  1252.9  1052.1 1301.04  1091.4 1310.15
#Mann= 3 , 0 , 0
       0     .08       0   533.7    .045       0   548.7     .08       0
Bank Sta=533.7,548.7
XS Rating Curve= 0 ,0
Exp/Cntr=0.3,0.1

Type RM Length L Ch R = 1 ,6123.1  ,426,436.3,446.6
XS GIS Cut Line= 2
     1677093.595      260862.619     1678110.578      260363.771
#Sta/Elev= 30
       0 1361.59    58.6  1384.4    68.4 1387.17    78.1 1384.44    97.6 1370.72
   175.8 1334.44   195.3 1319.49   273.4 1284.36     293  1270.7   371.1 1235.94
   410.1 1210.34   478.5 1184.69   488.2 1175.68   527.3 1158.21   585.9 1119.22
   605.4 1098.74   644.5  1071.6   683.6 1046.37   693.3 1044.17   696.4 1044.31
   711.4 1045.78   810.5 1055.11   859.3 1081.28   908.2 1084.64   927.7 1090.65
   986.3  1134.2  1005.8 1153.41  1083.9 1200.66  1103.4 1218.31  1132.7 1236.37
#Mann= 3 , 0 , 0
       0     .08       0   696.4    .045       0   711.4     .08       0
Bank Sta=696.4,711.4
XS Rating Curve= 0 ,0
Exp/Cntr=0.3,0.1

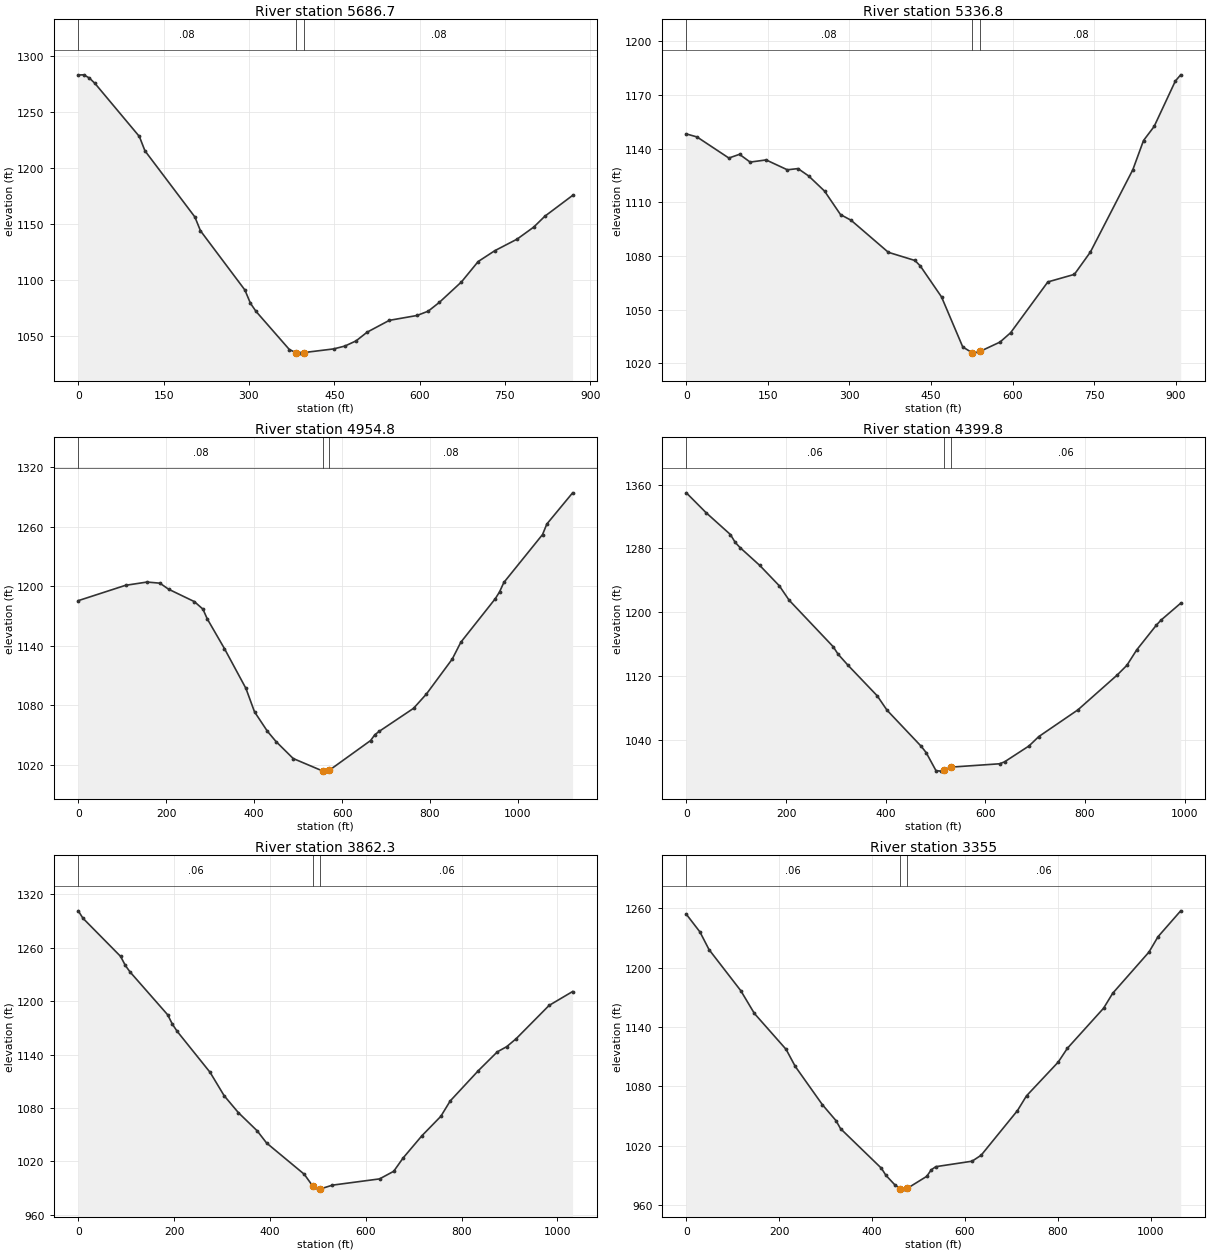
Type RM Length L Ch R = 1 ,5686.7  ,366.9,350,333.1
XS GIS Cut Line= 2
     1677267.062      260974.899     1678135.962      260978.453
#Sta/Elev= 30
       0 1283.24     9.8 1283.39    19.5 1280.53    29.3 1275.74   107.4  1228.2
   117.2  1215.4     205 1156.15   214.8 1143.83   292.9  1090.8   302.6 1078.99
   312.4  1071.7     371 1037.56   382.5 1034.74   390.5 1034.32   397.5 1034.87
   449.1 1038.11   468.6 1040.64   488.2 1045.25   507.7 1053.06   546.7 1063.65
   595.5 1068.02   615.1 1071.88   634.6 1079.71   673.6 1098.08   702.9 1116.29
   732.2 1126.01   771.3 1136.34   800.6 1147.13   820.1 1156.83   868.9 1175.48
#Mann= 3 , 0 , 0
       0     .08       0   382.5    .045       0   397.5     .08       0
Bank Sta=382.5,397.5
XS Rating Curve= 0 ,0
Exp/Cntr=0.3,0.1

Type RM Length L Ch R = 1 ,5336.8  ,369.4,381.9,394.5
XS GIS Cut Line= 2
     1677444.645       261619.93     1678117.909      261008.563
#Sta/Elev= 30
       0 1148.31    19.6 1146.62    78.2 1134.83    97.8  1136.9   117.4 1132.56
   146.7 1133.77   185.8 1128.25   205.4 1128.93   224.9 1124.83   254.2 1116.36
   283.6 1103.21   303.1 1100.03   371.6 1082.12   420.5 1077.55   430.3 1074.52
   469.4 1057.19   508.5 1029.19   525.4 1026.05     528 1025.75   540.4 1026.73
     577 1031.93   596.5 1037.14     665 1065.56   713.8 1069.78   743.2 1082.23
   821.4 1128.33     841 1144.62   860.5 1152.46   899.6  1177.9   909.4 1181.35
#Mann= 3 , 0 , 0
       0     .08       0   525.4    .045       0   540.4     .08       0
Bank Sta=525.4,540.4
XS Rating Curve= 0 ,0
Exp/Cntr=0.3,0.1

Type RM Length L Ch R = 1 ,4954.8  ,560.6,555,549.3
XS GIS Cut Line= 2
     1677457.963      261696.403     1678564.276       261496.51
#Sta/Elev= 30
       0 1185.33   107.5 1200.78   156.4 1204.08   185.7 1202.94   205.3 1196.89
     264 1184.37   283.5 1176.79   293.3 1167.02   332.4 1137.05   381.3  1096.9
   400.8 1073.32   430.1 1053.75   449.7 1043.38   488.8 1026.25   555.7  1013.7
   557.2 1013.55   570.7 1014.36   664.8 1044.38   674.5 1050.25   684.3  1053.6
   762.5 1076.84   791.8 1091.28   850.5 1126.49     870 1143.43   948.3 1187.27
     958 1194.13   967.8 1203.63  1055.8 1251.94  1065.6 1262.55  1124.2 1293.98
#Mann= 3 , 0 , 0
       0     .08       0   555.7    .045       0   570.7     .08       0
Bank Sta=555.7,570.7
XS Rating Curve= 0 ,0
Exp/Cntr=0.3,0.1

Type RM Length L Ch R = 1 ,4399.8  ,529.5,537.5,545.5
XS GIS Cut Line= 2
     1677640.129       262350.61     1678543.501      261940.448
#Sta/Elev= 30
       0 1349.57    39.3 1324.87    88.4 1297.32    98.2 1287.33     108 1280.83
   147.4 1258.54   186.6 1233.02   206.3 1214.98   294.7 1156.72   304.5 1147.36
   324.2 1133.62   383.1 1095.12   402.7 1077.14   471.5 1031.76   481.3 1023.95
     501 1001.35   510.8 1000.75   516.1 1001.96   531.1 1005.77   628.7 1009.96
   638.5 1012.36   687.6 1032.29   707.3 1044.06   785.8 1077.55   864.4 1121.07
   884.1 1133.37   903.7  1152.6     943 1183.56   952.8 1190.13   992.1 1211.23
#Mann= 3 , 0 , 0
       0     .06       0   516.1    .045       0   531.1     .06       0
Bank Sta=516.1,531.1
XS Rating Curve= 0 ,0
Exp/Cntr=0.3,0.1

Type RM Length L Ch R = 1 ,3862.3  ,503.9,507.3,510.7
XS GIS Cut Line= 2
     1677766.371      262673.843     1678795.559      262600.418
#Sta/Elev= 30
       0 1301.49     9.8 1293.16    88.4 1250.26    98.3 1240.06   108.1  1232.8
   186.7 1184.59   196.5 1174.05   206.4 1166.08   275.2 1119.92   304.6 1093.62
   334.1 1074.73   373.4 1054.26   393.1 1040.53   471.7 1005.42   489.8  991.83
   501.2   988.7   504.8  988.84   530.6  993.19   628.9  1000.2   658.4 1008.75
     678  1023.7   717.4 1048.79   756.7 1070.49   776.3  1087.8   835.3    1122
   874.6 1142.98   894.2 1148.82   913.9 1157.73   982.7 1195.17  1031.8 1210.79
#Mann= 3 , 0 , 0
       0     .06       0   489.8    .045       0   504.8     .06       0
Bank Sta=489.8,504.8
XS Rating Curve= 0 ,0
Exp/Cntr=0.3,0.1

Type RM Length L Ch R = 1 ,3355    ,467,470.5,473.9
XS GIS Cut Line= 2
     1677784.117      263106.035     1678845.158      263191.144
#Sta/Elev= 30
       0 1253.79    29.3 1235.92    48.8 1218.16   117.2 1176.66   146.5 1153.66
   214.8  1117.4   234.4 1100.28     293  1061.5   322.3 1045.43     332 1037.37
   419.9  997.45   429.7  990.26   449.2  980.53   460.6  976.86   468.8  976.33
   475.6  977.06   517.6  989.24   527.3  995.81   537.1  998.99   615.2 1004.52
   634.8 1010.57   712.9 1055.58   732.4  1070.5   800.8 1104.62   820.3 1118.44
   898.4 1158.97     918 1174.04   996.1 1215.64  1015.6 1231.14  1064.4 1257.25
#Mann= 3 , 0 , 0
       0     .06       0   460.6    .045       0   475.6     .06       0
Bank Sta=460.6,475.6
XS Rating Curve= 0 ,0
Exp/Cntr=0.3,0.1

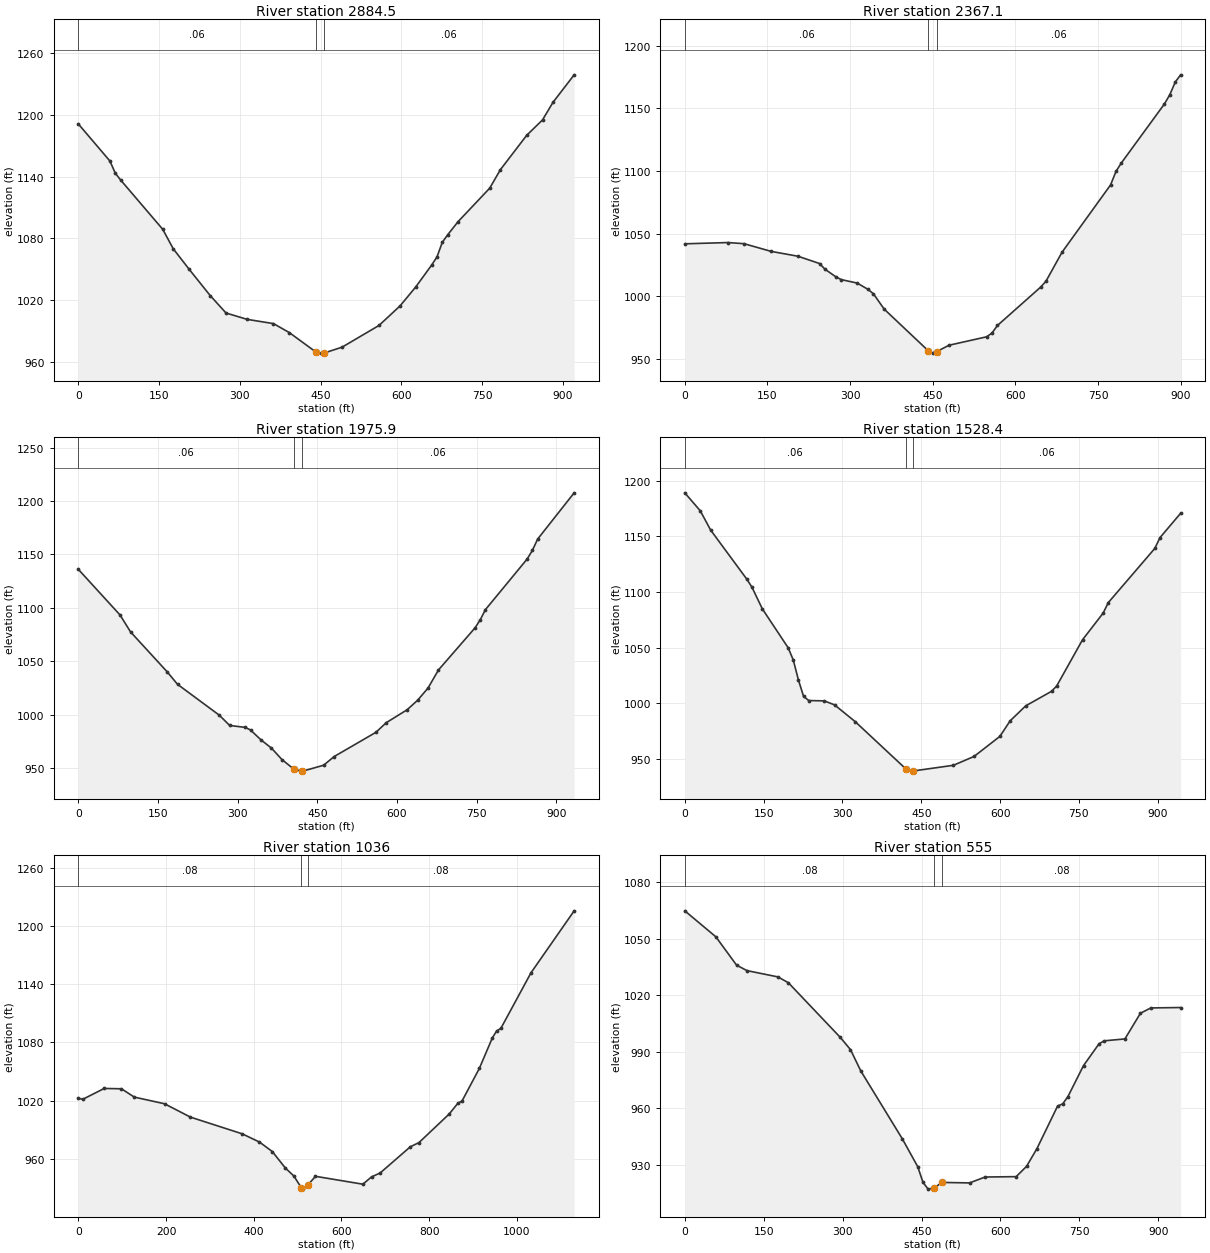
Type RM Length L Ch R = 1 ,2884.5  ,515.2,517.4,519.6
XS GIS Cut Line= 2
     1677710.784      263497.861     1678607.196      263710.098
#Sta/Elev= 30
       0 1191.39    58.8 1155.22    68.6 1143.51    78.4 1136.94   156.8 1088.84
   176.4 1069.82   205.8 1049.99     245 1024.33   274.4 1007.35   313.6 1001.17
   362.6  997.03     392  988.29   441.3  969.42   450.8   968.3   456.3  968.35
     490   974.1   558.6  995.24   597.8  1014.3   627.2 1032.94   656.6 1054.15
   666.4 1061.98   676.2 1076.15     686 1083.33   705.6 1096.32   764.4 1128.93
     784 1146.77     833  1180.3   862.4  1195.3     882 1212.52   921.2  1239.2
#Mann= 3 , 0 , 0
       0     .06       0   441.3    .045       0   456.3     .06       0
Bank Sta=441.3,456.3
XS Rating Curve= 0 ,0
Exp/Cntr=0.3,0.1

Type RM Length L Ch R = 1 ,2367.1  ,397.4,391.2,385
XS GIS Cut Line= 2
     1677596.659      263953.102     1678448.879      264242.272
#Sta/Elev= 30
       0 1041.85    78.3 1042.86   107.6 1041.95   156.5 1035.83   205.4 1031.94
   244.6 1026.12   254.3 1021.64   273.9 1015.57   283.7 1013.32     313 1010.51
   332.6 1005.48   342.4 1001.94   361.9  989.73   442.1  956.42     450  954.62
   457.1  955.79   479.3  960.89   547.8  967.65   557.6  970.68   567.4  976.67
   645.6  1007.2   655.4 1011.94   684.7 1035.17   772.8 1088.88   782.6 1099.65
   792.3 1106.37   870.6 1153.53   880.4 1160.95   890.2 1171.01   899.9 1176.71
#Mann= 3 , 0 , 0
       0     .06       0   442.1    .045       0   457.1     .06       0
Bank Sta=442.1,457.1
XS Rating Curve= 0 ,0
Exp/Cntr=0.3,0.1

Type RM Length L Ch R = 1 ,1975.9  ,452.3,447.6,442.8
XS GIS Cut Line= 2
     1677508.411      264448.406     1678440.246      264503.023
#Sta/Elev= 30
       0 1135.99    78.6 1093.22    98.3 1077.42     167 1040.19   186.7 1028.37
   265.3  999.47   284.9  989.83   314.4     988   324.2  985.55   343.9  976.31
   363.6  968.62   383.2  957.95   405.8  948.91   420.8  947.12   422.5  947.07
   461.8   952.6   481.5  960.69   560.1  983.37   579.7  992.43     619 1004.55
   638.7 1013.42   658.3 1024.85     678 1041.81   746.8  1081.2   756.6 1088.76
   766.4 1098.28     845 1145.72   854.8 1153.76   864.7 1164.35   933.4 1207.63
#Mann= 3 , 0 , 0
       0     .06       0   405.8    .045       0   420.8     .06       0
Bank Sta=405.8,420.8
XS Rating Curve= 0 ,0
Exp/Cntr=0.3,0.1

Type RM Length L Ch R = 1 ,1528.4  ,509.3,492.4,475.4
XS GIS Cut Line= 2
     1677516.608      264976.391     1678446.899      264819.054
#Sta/Elev= 30
       0 1189.15    29.5 1172.97    49.1 1155.77   117.9 1111.67   127.8 1104.39
   147.4 1085.04   196.6 1050.05   206.4 1039.05   216.2  1021.1     226 1006.34
   235.9  1002.6   265.4 1002.29     285   998.7   324.3  983.63   420.1  941.43
   432.4   939.2   435.1  939.38   511.1  944.44   550.4  952.38   599.5  970.38
   619.2  984.42   648.7  997.83   697.8 1010.87   707.6 1015.64   756.8 1057.16
   796.1 1081.16   805.9 1090.57   894.4 1139.24   904.2  1148.9   943.5 1170.79
#Mann= 3 , 0 , 0
       0     .06       0   420.1    .045       0   435.1     .06       0
Bank Sta=420.1,435.1
XS Rating Curve= 0 ,0
Exp/Cntr=0.3,0.1

Type RM Length L Ch R = 1 ,1036    ,477.9,481,484.1
XS GIS Cut Line= 2
     1677847.321      265715.462     1678548.993      264828.797
#Sta/Elev= 30
       0 1022.69     9.8 1021.36      59 1032.62    98.3 1032.27   127.8 1023.68
   196.6 1016.84   255.6 1003.08   373.6  985.88     413  977.39   442.4  967.58
     472  950.67   491.6  942.34   508.3  930.43   511.3  928.87   523.3  933.06
   540.8  942.07   648.9  933.95   668.6  941.47   688.3  945.52   757.1  972.52
   776.8  976.83   845.6 1006.23   865.2 1017.18   875.1 1019.76   914.4  1053.2
   943.9 1084.49   953.7 1091.78   963.6 1094.57  1032.4 1151.91  1130.7 1215.66
#Mann= 3 , 0 , 0
       0     .08       0   508.3    .045       0   523.3     .08       0
#XS Ineff= 2 , 0
                           544.2          941.56
Permanent Ineff=
       F       F
Bank Sta=508.3,523.3
XS Rating Curve= 0 ,0
Exp/Cntr=0.3,0.1

Type RM Length L Ch R = 1 ,555     ,223.4,225.9,228.4
XS GIS Cut Line= 3
     1678174.735      265946.436     1678827.467       265333.33
     1678840.473      265288.269
#Sta/Elev= 30
       0 1064.87      59 1051.08    98.4 1036.02   118.1 1033.11   177.1 1029.76
   196.8 1026.68   295.2  997.74   314.9  991.14   334.6  979.76   413.3   943.8
   442.8  928.92   452.7  920.63   462.5  917.02     474  917.68     489  920.58
   541.2  920.32   570.8  923.45   629.8  923.65   649.5   929.1   669.2  938.49
   708.5  961.12   718.4  962.36   728.2  966.18   757.8  982.64   787.3  994.22
   797.1  995.81   836.5  996.81     866 1010.45   885.7 1013.28   942.4  1013.5
#Mann= 3 , 0 , 0
       0     .08       0     474    .045       0     489     .08       0
Bank Sta=474,489
XS Rating Curve= 0 ,0
Exp/Cntr=0.3,0.1

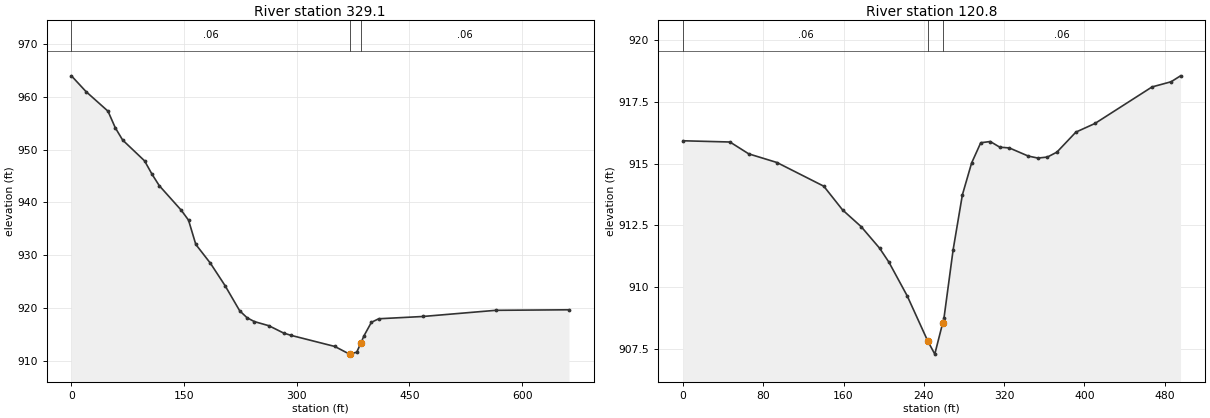
Type RM Length L Ch R = 1 ,329.1   ,209.1,208.3,207.5
XS GIS Cut Line= 2
      1678394.46      265975.322     1678922.111      265574.857
#Sta/Elev= 30
       0  963.95    19.5  960.96    48.7  957.26    58.4  954.12    68.2   951.8
    97.4  947.86   107.2  945.36   116.9  943.18   146.1  938.54   155.9  936.65
   165.6  932.05   185.1  928.48   204.6  924.24     224   919.5   233.8  918.18
   243.5  917.45     263  916.66   282.5  915.28   292.2  914.85   350.7  912.74
   370.2  911.29   370.4   911.3   379.9  911.66   385.4  913.42   389.6  914.78
   399.4  917.31   409.1  917.98   467.6  918.41     565  919.58   662.4  919.68
#Mann= 3 , 0 , 0
       0     .06       0   370.4    .045       0   385.4     .06       0
Bank Sta=370.4,385.4
XS Rating Curve= 0 ,0
Exp/Cntr=0.3,0.1

Type RM Length L Ch R = 1 ,120.8   ,121.5,120.8,120.2
XS GIS Cut Line= 4
     1678583.521      266006.259     1678746.801       265965.01
     1678846.487      265884.229     1678870.549      265686.575
#Sta/Elev= 30
       0  915.93    46.8  915.88    65.5   915.4    93.6  915.05   140.3  914.09
     159  913.13   177.6  912.45   195.9  911.58   205.1  911.02   223.4  909.65
   243.9  907.82   250.9  907.29   258.9  908.57   260.1  908.76   269.2  911.52
   278.4  913.74   287.6  915.03   296.7  915.85   306.2   915.9   315.7  915.67
   325.2  915.64   344.1  915.31   353.6  915.23   363.1  915.27   372.6  915.47
   391.5  916.28   410.5  916.63   467.4  918.11   486.4  918.32   495.8  918.56
#Mann= 3 , 0 , 0
       0     .06       0   243.9    .045       0   258.9     .06       0
Bank Sta=243.9,258.9
XS Rating Curve= 0 ,0
Exp/Cntr=0.3,0.1

Chan Stop Cuts=-1
Use User Specified Reach Order=0
Composite Channel Slope=5